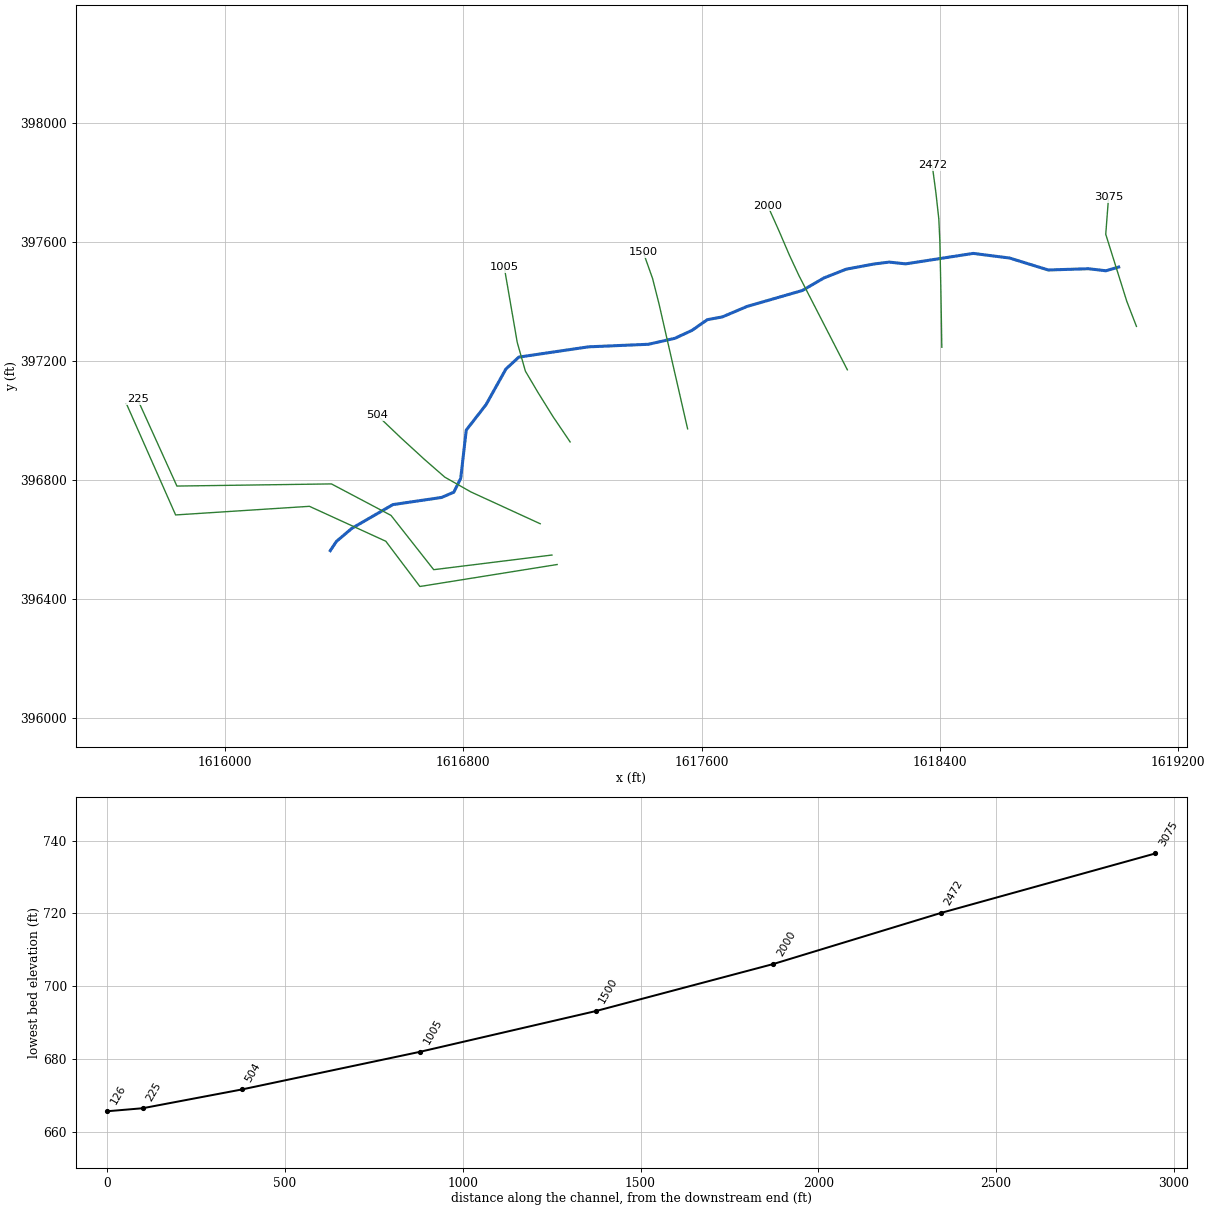
--- MONEYRN.prj (project) ---

Proj Title=MONEYRN
Current Plan=p01
Default Exp/Contr=0,0
English Units
Geom File=g01
Flow File=f01
Plan File=p01
BEGIN DESCRIPTION:
---------- MODELED AS PART OF WVEMD CTP PROGRAM, 2023----------
Stream Name: Money Run
Flood Zone:  AFH
Wetzel County, WV
HEC-RAS Version: RAS 6.3
Vertical Datum: NAVD88
Projection: NAD 1983 StatePlane West Virginia S FIPS 4702 (US Feet)
Terrain: 1-meter West Virginia FEMA R3 South Central (collected 2018-2020)
Land Use: 2019 NLCD
Hydrologic Method:
WV SIR2010-5033 regression equations
Additional Model Notes:
Leveraged XS
END DESCRIPTION:
DSS Export Rating Curves= 0
DSS Export Rating Curve Sorted= 0
DSS Export Volume Flow Curves= 0
DXF OffsetX= 0
DXF OffsetY= 0
DXF ScaleX= 0
DXF ScaleY= 0

--- MONEYRN.p01 (plan) ---

Plan Title=Floodplain
Program Version=6.30
Short Identifier=Floodplain
Geom File=g01
Flow File=f01
Subcritical Flow
K Sum by GR= 0
Std Step Tol= 0.01
Critical Tol= 0.01
Num of Std Step Trials= 20
Max Error Tol= 0.3
Flow Tol Ratio= 0.001
Split Flow NTrial= 30
Split Flow Tol= 0.02
Split Flow Ratio= 0.02
Log Output Level= 0
Friction Slope Method= 1
Unsteady Friction Slope Method= 2
Unsteady Bridges Friction Slope Method= 1
Parabolic Critical Depth
Global Vel Dist= 0 , 0 , 0
Global Log Level= 0
CheckData=True
Encroach Param=-1 ,0,0, 0
Mapping Interval=1HOUR
Computation Time Step Use Courant=        0
Computation Time Step Use Time Series=    0
Computation Time Step Count To Double=0
Computation Time Step Max Doubling=0
Computation Time Step Max Halving=0
Computation Time Step Residence Courant=0
Run HTab= 0
Run UNet= 0
Run Sediment= 0
Run PostProcess= 0
Run WQNet= 0
Run RASMapper= 0
UNET Theta= 0
UNET Theta Warmup= 0
UNET ZTol= 0
UNET ZSATol= 0
UNET MxIter= 0
UNET Max Iter WO Improvement= 0
UNET MaxInSteps= 0
UNET DtIC= 0
UNET DtMin= 0
UNET MaxCRTS= 0
UNET WFStab= 0
UNET SFStab= 0
UNET WFX= 1
UNET SFX= 1
UNET Gravity=32.17405
UNET 1D Methodology=Finite Difference
UNET DSS MLevel= 1
UNET Pardiso=0
UNET DZMax Abort= 0
UNET Use Existing IB Tables= 0
UNET Froude Reduction=False
UNET Froude Limit= 0
UNET Froude Power= 0
UNET D1 Cores= 0
UNET WindReference=Eulerian
UNET WindDragFormulation=Hsu (1988)
UNET D2 Coriolis=0
UNET D2 Cores= 0
UNET D2 Theta= 1
UNET D2 Theta Warmup= 1
UNET D2 Z Tol= 0.01
UNET D2 Volume Tol= 0.01
UNET D2 Max Iterations= 20
UNET D2 Equation= 0
UNET D2 RampUpFraction=0.1
UNET D2 TimeSlices= 1
UNET D2 Turbulence Formulation=Non-Conservative (original)
UNET D2 Eddy Viscosity=0.3
UNET D2 Transverse Eddy Viscosity=0.1
UNET D2 Smagorinsky Mixing=0
UNET D2 BCVolumeCheck=0
UNET D2 Cores=0
UNET D2 SolverType=PARDISO (Direct)
UNET D2 Minimum Iterations= 3
UNET D2 Maximum Iterations= 30
UNET D2 Restart Number= 10
UNET D2 Relaxation Coeff=1.3
UNET D2 SOR Precondition Iterations= 10
UNET D2 ILUT Maximum Fill= 8
UNET D2 ILUT Tolerance=1E-08
UNET D2 Convergence Tolerance=0.00001
UNET D1D2 MaxIter= 0
UNET D1D2 ZTol=0.01
UNET D1D2 QTol=0.1
UNET D1D2 MinQTol=1
Write IC File= 0
Write IC File at Fixed DateTime=0
Write IC File at Sim End=0
Echo Input=False
Echo Parameters=False
Echo Output=False
Write Detailed= 0
HDF Write Warmup=0
HDF Write Time Slices=0
HDF Flush=0
HDF Compression= 1
HDF Chunk Size= 1
HDF Spatial Parts= 1
HDF Use Max Rows=0
HDF Fixed Rows= 1
Calibration Method= 0
Calibration Iterations= 20
Calibration Max Change=0.05
Calibration Tolerance=0.2
Calibration Maximum=1.5
Calibration Minimum=0.5
Calibration Optimization Method= 1
WQ AD Non Conservative
WQ ULTIMATE=-1
WQ Max Comp Step=1HOUR
WQ Output Interval=15MIN
WQ Output Selected Increments= 0
WQ Output face flow=0
WQ Output face velocity=0
WQ Output face area=0
WQ Output face dispersion=0
WQ Output cell volume=0
WQ Output cell surface area=0
WQ Output cell continuity=0
WQ Output cumulative cell continuity=0
WQ Output face conc=0
WQ Output face dconc_dx=0
WQ Output face courant=0
WQ Output face peclet=0
WQ Output face adv mass=0
WQ Output face disp mass=0
WQ Output cell mass=0
WQ Output cell source sink temp=0
WQ Output nsm pathways=0
WQ Output nsm derived pathways=0
WQ Create Restart=0
WQ Fixed Restart=0
WQ System Summary=0
WQ Write To DSS=0
Sorting and Armoring Iterations= 10
XS Update Threshold= 0.02
Bed Roughness Predictor= 0
Hydraulics Update Threshold= 0.02
Energy Slope Method= 1
Volume Change Method= 1
Sediment Retention Method= 0
Sediment TS Multiplier= 1
Warm Up Method= 0
XS Weighting Method= 0
Number of US Weighted Cross Sections= 1
Number of DS Weighted Cross Sections= 1
Upstream XS Weight=0
Main XS Weight=1
Downstream XS Weight=0
Number of DS XS's Weighted with US Boundary= 1
Upstream Boundary Weight= 1
Weight of XSs Associated with US Boundary= 0
Number of US XS's Weighted with DS Boundary= 1
Downstream Boundary Weight= 0.5
Weight of XSs Associated with DS Boundary= 0.5
Percentile Method= 0
Sediment Output Level= 3
Mass or Volume Output= 0
Output Increment Type= 1
Profile and TS Output Increment= 1
Transport Output Increment 1
XS Output Flag= 0
XS Output Increment= 10
Read HDF5 Sediment Hotstart= 0
Sediment Hotstart Type= 0
Write Gradation File= 0
Read Gradation Hotstart= 0
Write HDF5 File= 1
Write Binary Output= 1
Write DSS Sediment File= 0
DSS Sediment Output Type= 1
SV Curve= 0
Specific Gage Flag= 0
Subcell Erosion Methods= 0
Subcell Deposition Methods= 0
Advection Scheme= 1
Matrix Solver= 0
Implicit Weighting Factor= 1
Maximum Outer Loop Convergence Iterations= 5
Convergence Maximum Absolute= 0.001
Convergence RMSE= 0.0001
Grain Fractions Max Abs Error= 0.001
Max Subgrid Regions= 1
Max Subgrid Length Scale= 3.402823E+38
Initial Layer Thickness= 3.402823E+38
Min Layer Thickness= 3.402823E+38
Max Layer Thickness= 3.402823E+38
Number of Layers= 5

--- MONEYRN.f01 (steady flow) ---

Flow Title=Flow
Program Version=4.00
Number of Profiles=1
Profile Names=F01pct
River Rch & RM=MONEYRN,Main,3075
     743
River Rch & RM=MONEYRN,Main,504
     911
Boundary for River Rch & Prof#=MONEYRN,Main      ,1
Up Type=0
Dn Type=3
Dn Slope=0.027257

--- MONEYRN.g01 (geometry) ---

Geom Title=Geometry
Program Version=6.31

River Reach=MONEYRN         ,Main
Reach XY= 30
     1619000.458      397514.941     1618957.405      397502.452
     1618899.234      397509.353     1618764.158      397505.081
     1618634.012      397545.281     1618512.226      397560.847
     1618285.272       397525.72     1618229.533      397531.609
     1618178.001      397525.089     1618085.873      397507.841
     1618011.413      397478.605     1617938.216      397436.117
     1617753.286       397382.72     1617669.583      397347.287
     1617619.258      397338.044     1617567.906      397302.097
     1617510.392      397275.394     1617421.553      397255.367
     1617219.837      397246.702     1616986.347      397212.199
     1616943.018      397172.081     1616876.421      397052.527
     1616809.824      396966.673      1616791.37      396804.594
     1616768.101      396758.057      1616727.18      396740.404
     1616563.496      396716.333      1616426.29      396636.898
     1616374.136      396592.768     1616353.383      396561.649

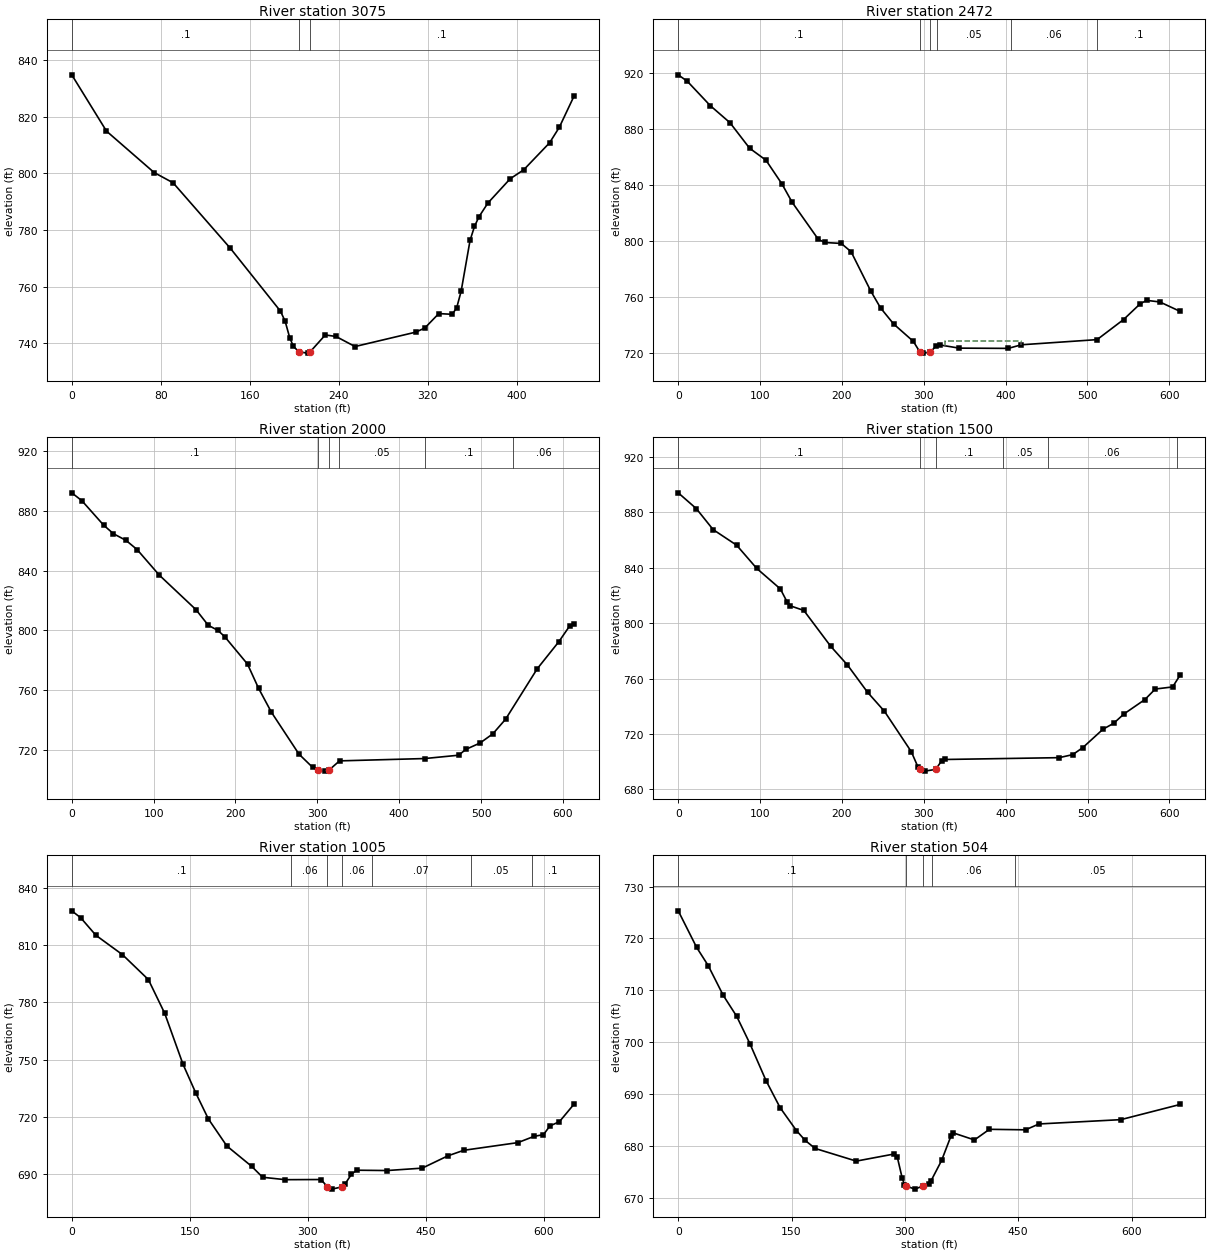
Type RM Length L Ch R = 1 ,3075    ,602.9,603.3,600.1
XS GIS Cut Line= 4
1619060.15258611397315.4435242241619027.81108224397399.542274001
1618957.07485915397625.1952064591618966.53751778397749.523709553
#Sta/Elev= 30
       0  834.74    31.2  814.87      74  800.25    91.1  796.61   142.6  773.47
   187.6  751.29   191.8  747.72   195.9  741.93   199.2  738.87   204.3  736.92
   211.9  736.48   214.2  736.91   227.9   742.9   237.5  742.36   254.6  738.81
   309.1  743.88   317.3  745.34   329.9  750.44     342  750.18     346  752.51
     350  758.35     358  776.28     362  781.22     366  784.62   374.1   789.5
   394.1  798.05   406.2  801.19   429.5  810.74   438.2  816.19   451.3  827.09
#Mann= 3 ,-1,0
       0      .1       0   204.3    .045       0   214.2      .1       0
Bank Sta=204.3,214.2
XS Rating Curve= 0 ,0
Exp/Cntr(USF)=0,0
Exp/Cntr=0.3,0.1

Type RM Length L Ch R = 1 ,2472    ,469.2,471.7,475.3
XS GIS Cut Line= 6
1618406.68162055397245.3296703381618403.73543222397426.555029674
1618400.10059697397601.5172781781618396.57534155397676.481039001
1618386.92312988397763.859801261 1618374.4779448397857.325493588
#Sta/Elev= 30
       0  918.47    11.2  913.81    39.2  896.48    63.2  884.36    87.2  866.17
   107.2  857.63   126.7  840.74   139.2  827.63   171.2  801.21   179.2  798.99
   199.2   798.3   211.2  792.43   235.2  764.46   247.2  752.38   263.2  740.92
   287.3  728.51  295.24  720.97   299.3  720.15   308.2  720.97   315.3  725.44
   319.3  726.01   343.3  723.71   403.3  723.53   419.3   726.1   511.8  729.77
   544.1  744.05   564.3  755.21   572.3  757.75   588.5  756.62   613.5  749.83
#Mann= 6 ,-1,0
       0      .1       0  295.24    .045       0   308.2      .1       0
  316.25     .05       0  406.25     .06       0   511.3      .1       0
#XS Ineff= 1 ,-1
  325.91     419  728.62
Permanent Ineff=
       T
Bank Sta=295.24,308.2
XS Rating Curve= 0 ,0
Exp/Cntr(USF)=0,0
Exp/Cntr=0.3,0.1

Type RM Length L Ch R = 1 ,2000    ,501.7,500,497.5
XS GIS Cut Line= 6
1618089.47300668 397169.515342251618006.73039001397330.776830763
1617926.84144217397486.4776348321617895.13350034397554.504729763
1617860.58173217397635.1223506781617822.10510309397721.319028676
#Sta/Elev= 30
       0  891.89    12.4  886.61    38.9  870.33    50.8  864.63    66.3  860.13
    79.8  854.03   106.8  837.03   151.8  813.88   166.7  803.51   178.7     800
     187  795.78   214.7  777.58   228.2  761.44   243.9  745.45   277.6  717.47
   294.4  708.56   300.4  706.94   309.1  706.13  314.52  706.92   327.1  712.97
   431.3  714.53   472.7  716.76   481.4  720.64   498.8  724.89   514.4  731.01
     530  740.78   568.7  774.48     595  792.48   608.2  802.94   613.4  804.38
#Mann= 6 ,-1,0
       0      .1       0   300.4    .045       0  314.52      .1       0
  326.25     .05       0   431.3      .1       0  539.01     .06       0
Bank Sta=300.4,314.52
XS Rating Curve= 0 ,0
Exp/Cntr(USF)=0,0
Exp/Cntr=0.3,0.1

Type RM Length L Ch R = 1 ,1500    ,494.9,494.7,495.6
XS GIS Cut Line= 6
1617553.12401375396971.0134426651617532.23461984397062.406304508
1617473.74392317397318.3067113461617457.03201434397391.421394512
1617435.58619109397476.2758835851617403.95338035397565.398080677
#Sta/Elev= 30
       0  893.97    22.1  882.57    42.6  867.45    71.3  856.21    95.9  839.44
   124.7  824.67   132.9  815.38     137  812.43   153.4  809.13   186.2   783.3
   206.7  769.78   231.3  750.06   251.9  736.36   284.7  707.21   292.9   696.1
  295.06694.5582   301.1   693.2   314.5  694.45   321.6  700.53   325.7   701.6
   465.4  702.92   481.9  705.11   494.3  710.22     519   723.5   531.8  727.66
   544.5  734.46     570  744.82   582.7  752.42   603.9  753.94   613.3  762.67
#Mann= 6 ,-1,0
       0      .1       0  295.06    .045       0   314.5      .1       0
  396.25     .05       0  451.25     .06       0  608.77      .1       0
Bank Sta=295.06,314.5
XS Rating Curve= 0 ,0
Exp/Cntr(USF)=0,0
Exp/Cntr=0.3,0.1

Type RM Length L Ch R = 1 ,1005    ,495,501,508
XS GIS Cut Line= 6
1617158.64875284396927.1300002491617101.06389426397012.356535837
1617050.28151551397094.1122778361617008.41512942397165.127555758
1616981.03427868397262.0210627621616937.49597992397514.545492083
#Sta/Elev= 30
       0  828.12    11.4  824.46    30.7  815.27    64.5   805.1    97.4  792.03
   118.2   774.3   141.4  747.63   157.7   732.5   173.7  718.88   197.2  704.67
   228.7  694.01   242.7  688.25   271.6  686.98     317  687.06  325.18683.1777
   330.8  682.02   343.3  683.17   347.4  684.63   355.7  689.83   362.3  691.95
     401  691.78   445.7  693.04   478.1  699.46   498.4   702.4   567.4  706.44
   587.7   709.7   599.9  710.63     608  715.17   620.2  717.45   638.5  726.51
#Mann= 7 ,-1,0
       0      .1       0   279.1     .06       0  325.18    .045       0
   343.3     .06       0  381.54     .07       0  507.23     .05       0
  584.73      .1       0
Bank Sta=325.18,343.3
XS Rating Curve= 0 ,0
Exp/Cntr(USF)=0,0
Exp/Cntr=0.3,0.1

Type RM Length L Ch R = 1 ,504     ,278.6,279.1,273.5
BEGIN DESCRIPTION:
Structure 1 XS 4
END DESCRIPTION:
XS GIS Cut Line= 6
1617058.29396668396652.0140806731616825.44567908396758.998446763
1616737.84349209396808.6781374221616670.73699901396867.301379755
1616591.73125151396939.6539253441616511.11789568397016.548456594
#Sta/Elev= 30
       0  725.33    24.4  718.27    39.6  714.79    59.6  709.03    77.4  704.99
    94.8  699.75   116.2  692.61   134.8   687.4   156.5  682.97   167.9   681.1
   181.2  679.53   235.7  677.09   285.4  678.45     290  677.84   296.5   673.8
   299.4  672.56  301.21672.3276     313  671.69   324.2  672.29   331.7  672.66
   334.6  673.28   348.6  677.21   360.9  681.88   363.8  682.54   392.1  681.17
   411.9  683.22   459.7  683.12   477.5  684.25   585.8  685.08   664.6  688.02
#Mann= 5 ,-1,0
       0      .1       0  301.21    .045       0   324.2      .1       0
  336.25     .06       0  446.06     .05       0
Bank Sta=301.21,324.2
XS Rating Curve= 0 ,0
Exp/Cntr(USF)=0,0
Exp/Cntr=0.3,0.1

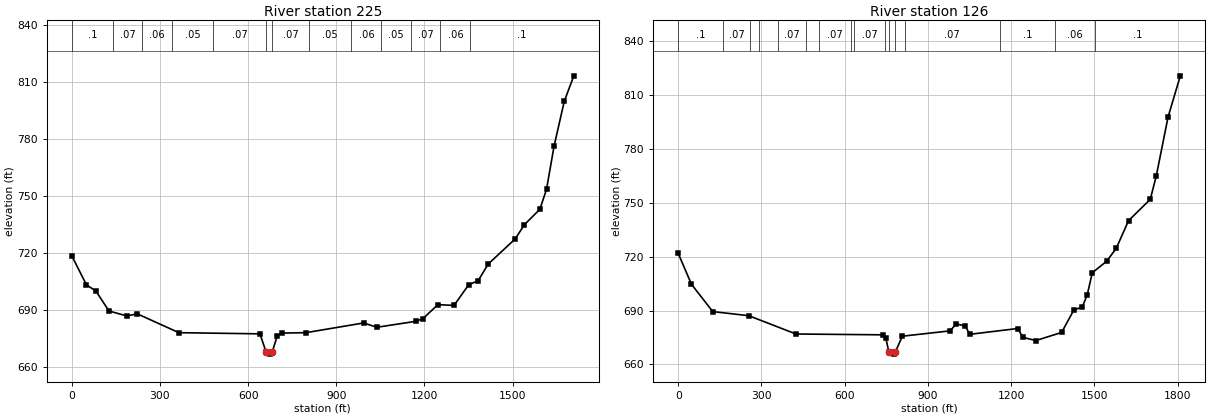
Type RM Length L Ch R = 1 ,225     ,96.8,99.1,99.7
BEGIN DESCRIPTION:
Structure 1 XS 3
END DESCRIPTION:
XS GIS Cut Line= 6
1617097.70216821396546.8434227031616700.64091821396497.573048615
1616557.17718189396680.1632584691616357.19742824396785.949649893
1615838.40937167396778.7040066441615706.53866456397069.978865221
#Sta/Elev= 30
       0  718.38      50  703.05    82.2  699.78   126.6  689.27     187  686.69
   223.3  687.75   364.4  677.85   640.2  677.23   661.4  667.54   673.2  666.54
   681.7  667.58   699.3   676.3   713.6  677.61   797.1  677.86   993.3  682.98
  1037.6  680.69  1170.2  683.82  1194.2  685.18  1245.5  692.61  1300.5  692.22
  1350.2  703.06  1382.5  705.25  1416.7  714.02  1508.9  727.32  1539.7  734.73
  1592.4  742.87  1615.2  753.42  1640.7  776.06  1675.6  799.86  1708.1  813.23
#Mann= 13 ,-1,0
       0      .1       0     140     .07       0     240     .06       0
     340     .05       0  480.21     .07       0   661.4    .045       0
   681.7     .07       0  807.24     .05       0  951.13     .06       0
 1053.54     .05       0 1154.25     .07       0 1254.25     .06       0
 1355.89      .1       0
Bank Sta=661.4,681.7
XS Rating Curve= 0 ,0
Exp/Cntr(USF)=0,0
Exp/Cntr=0.3,0.1

Type RM Length L Ch R = 1 ,126     ,,,
BEGIN DESCRIPTION:
Structure 1 XS 2
END DESCRIPTION:
XS GIS Cut Line= 6
  1617115.091712396514.9625924111616654.26880142396441.057031279
 1616539.7876381396593.2155394911616283.29186711396710.594960112
1615834.06198573396681.6123871191615668.86131967397055.487578725
#Sta/Elev= 30
       0  721.81    47.6  704.65   124.5  689.41   254.2  687.13   424.3  676.93
   739.2  676.47   748.1  674.68   759.1  666.82     777  665.72  782.16   666.8
   807.5  675.71   980.1  678.69  1001.7   682.6  1034.3  681.34  1050.6  676.76
  1222.8  679.98  1242.9  674.99    1289   673.3  1381.5  677.79  1425.6   690.3
  1456.2  692.02    1474  698.87  1492.2  711.08  1543.7  717.43  1578.7  724.73
  1622.6  740.06  1701.1  751.96    1723  765.21  1765.1  797.78  1809.3  820.76
#Mann= 16 ,-1,0
       0      .1       0     160     .07       0     260     .06       0
     290     .05       0     360     .07       0     460    .025       0
  506.71     .07       0  621.65    .025       0  631.65     .07       0
  745.66      .1       0   759.1    .045       0  782.16      .1       0
  815.66     .07       0 1159.29      .1       0 1356.55     .06       0
 1500.53      .1       0
Bank Sta=759.1,782.16
XS Rating Curve= 0 ,0
Exp/Cntr(USF)=0,0
Exp/Cntr=0.3,0.1
LCMann Table=0

Chan Stop Cuts=-1
Use User Specified Reach Order=0
Composite Channel Slope=5